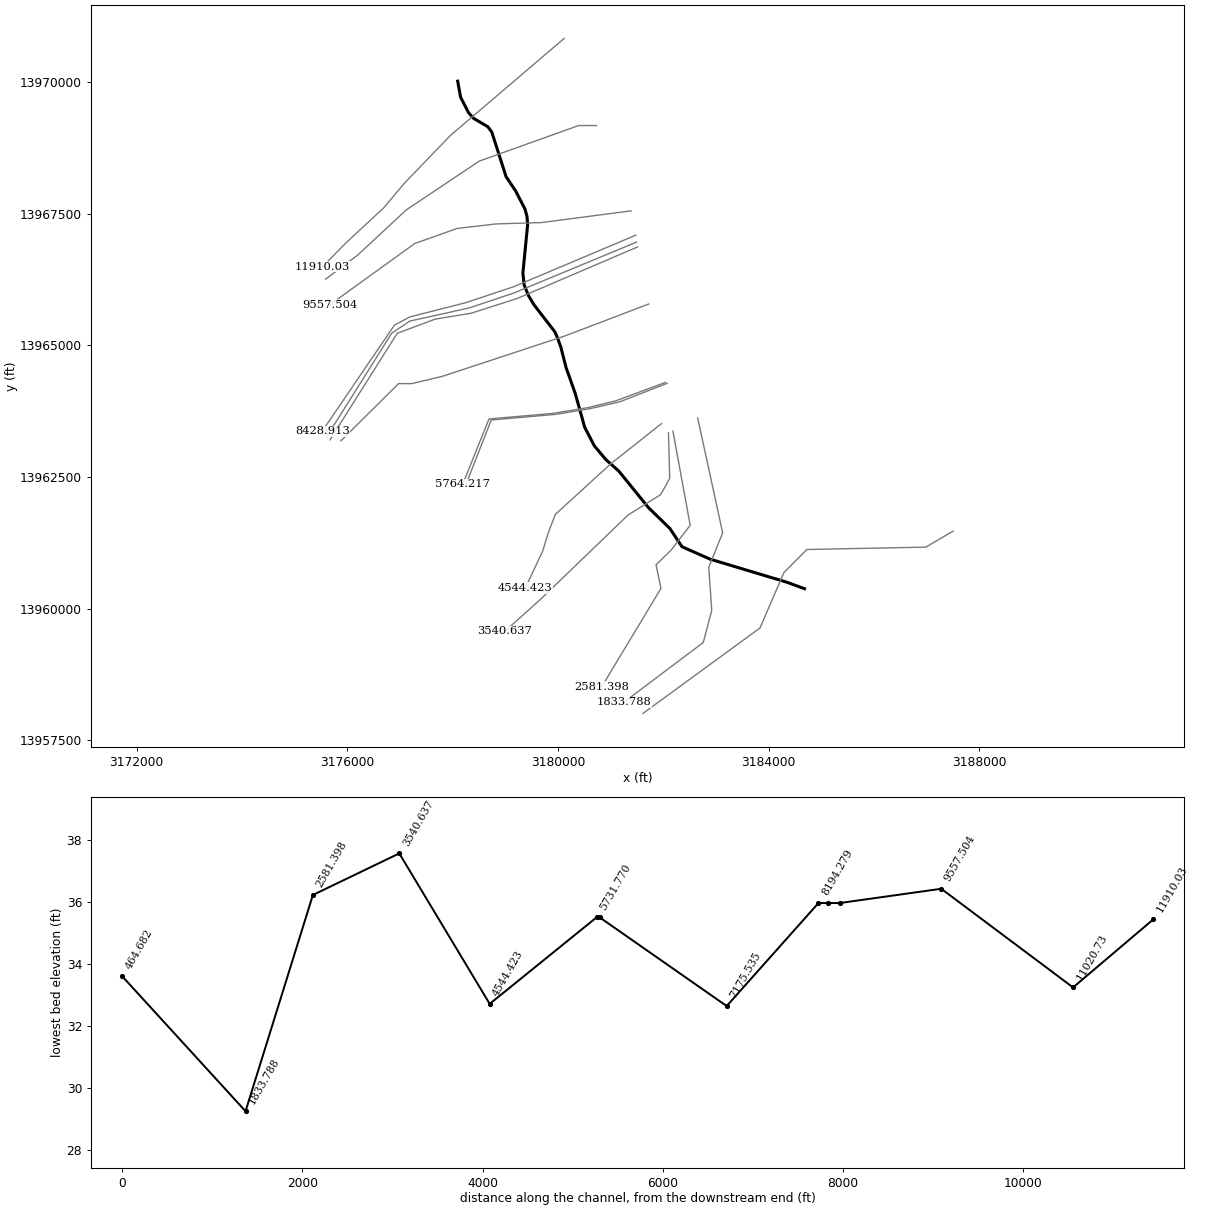
--- G103-80-03.prj (project) ---

Proj Title=G103-80-03
Current Plan=p02
Default Exp/Contr=.3,.1
English Units
Geom File=g01
Flow File=f01
Flow File=f02
Plan File=p01
Plan File=p02
Y Axis Title=Elevation
X Axis Title(PF)=Main Channel Distance
X Axis Title(XS)=Station
BEGIN DESCRIPTION:
San Jacinto River Watershed
Caney Creek
HCFCD Unit G103-80-03
(Flood Hazard, Floodway) Model
10, 2, 1, 0.2% Event
Filename g1038003.prj
Prepared by:  FTN Associates Ltd.   DATE:  June 2003
Reviewed by: 	 DATE:
STATUS (Final RAS)
Starting condition is normal depth, channel slope = 0.0044, taken form FIS due to large difference in invert elevations at downstream end.
Blocks are placed at adjacent watersheds:  LOB= EF San Jacinto River
END DESCRIPTION:
DSS Export Rating Curves= 0
DSS Export Rating Curve Sorted= 0
DSS Export Volume Flow Curves= 0
DXF OffsetX= 0
DXF OffsetY= 0
DXF ScaleX= 1
DXF ScaleY= 10

--- G103-80-03.p02 (plan) ---

Plan Title=Floodway
Version=Version 3.0.1  Mar 2001
Short Identifier=Floodway0607
Geom File=g01
Flow File=f02
Subcritical Flow
K Sum by GR= 0
Std Step Tol= 0.01
Critical Tol= 0.01
Num of Std Step Trials= 20
Max Error Tol= 0.3
Flow Tol Ratio= 0.001
Split Flow NTrial= 30
Split Flow Tol= 0.02
Split Flow Ratio= 0.02
Log Output Level= 0
Friction Slope Method= 1
Unsteady Friction Slope Method= 2
Parabolic Critical Depth
Global Vel Dist= 0 , 0 , 0
Global Log Level= 0
CheckData=True
Encroach Param= 0 ,0,0, 2
Encroach River=G103-80-03
Encroach Reach=G103-80-03_0005
Encroach Node=11910.03
       1     876    4566
Encroach Node=11020.73
       1 1345.18    5064
Encroach Node=9557.504
       1 1416.78    5003
Encroach Node=8428.913
       1    1409    5136
Encroach Node=8304.972
       1    1472    5153
Encroach Node=8194.279
       1    1497    5122
Encroach Node=7175.535
       1 1400.39    4802
Encroach Node=5764.217
       1 1158.19    3605
Encroach Node=5731.770
       1    1200    3662
Encroach Node=4544.423
       1    1072 3167.71
Encroach Node=3540.637
       1    1350    2900
Encroach Node=2581.398
       1    2000    3300
Encroach Node=1833.788
       1    2572    3450
Encroach Node=464.682
       1 3515.11    4362
Computation Interval=1HOUR
Output Interval=1HOUR
Run HTab= 0
Run UNet= 0
Run PostProcess= 0
UNET Theta= 1
UNET ZTol= 0.02
UNET ZSATol= 0.1
UNET MxIter= 20
UNET MaxInSteps= 20
UNET DtIC= 0
UNET DtMin= 0
UNET MaxCRTS= 20
UNET WFStab= 2
UNET SFStab= 1
UNET WFX= 1
UNET SFX= 1
UNET Convert EG Bridges=-1
UNET Use Existing IB Tables=-1
Instantaneous Interval=1HOUR
Write IC File= 0
Write Velocity= 0
Write Detailed= 0

--- G103-80-03.p01 (plan) ---

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Plan Title=FEMA Effective June 2007
Short Identifier=FEMAeff0607
Geom File=g01
Flow File=f01
Encroach Param=-1 ,0,0, 0
IC Time=0

--- G103-80-03.f02 (steady flow) ---

Flow Title=Floodway
Version=Version 3.0.1  Mar 2001
Number of Profiles= 2
Profile Names=1PCT_100yr, 1PCTFloodway_100yrFW
River Rch & RM=G103-80-03,G103-80-03_0005     ,11910.03
   75050   75050
River Rch & RM=G103-80-03,G103-80-03_0005     ,9557.504
   74370   74370
River Rch & RM=G103-80-03,G103-80-03_0005     ,8428.913
   75652   75652
River Rch & RM=G103-80-03,G103-80-03_0005     ,7175.535
   75432   75432
River Rch & RM=G103-80-03,G103-80-03_0005     ,5764.217
   75832   75832
River Rch & RM=G103-80-03,G103-80-03_0005     ,4544.423
   74912   74912
River Rch & RM=G103-80-03,G103-80-03_0005     ,3540.637
   75723   75723
River Rch & RM=G103-80-03,G103-80-03_0005     ,1833.788
   76372   76372
River Rch & RM=G103-80-03,G103-80-03_0005     ,464.682
   76630   76630
Boundary for River Rch & Prof#=G103-80-03,G103-80-03_0005     , 1
Up Type= 0
Dn Type= 3
Dn Slope=.0044
Boundary for River Rch & Prof#=G103-80-03,G103-80-03_0005     , 2
Up Type= 0
Dn Type= 3
Dn Slope=.0044
DSS Import GetInterval= 0
DSS Import GetPeak= 0
DSS Import FillOption= 0

--- G103-80-03.f01 (steady flow) ---

Flow Title=FEMA Effective June 2007
Version=Version 3.0.1  Mar 2001
Number of Profiles= 4
Profile Names=10PCT_10yr, 2PCT_50yr, 1PCT_100yr, 0.2PCT_500yr
River Rch & RM=G103-80-03,G103-80-03_0005     ,11910.03
   23310   54450   75050  137180
River Rch & RM=G103-80-03,G103-80-03_0005     ,9557.504
   23310   54130   74370  135340
River Rch & RM=G103-80-03,G103-80-03_0005     ,8428.913
   23695   54985   75652  137605
River Rch & RM=G103-80-03,G103-80-03_0005     ,7175.535
   23705   54855   75432  136935
River Rch & RM=G103-80-03,G103-80-03_0005     ,5764.217
   23845   55044   75832  137705
River Rch & RM=G103-80-03,G103-80-03_0005     ,4544.423
   23585   54334   74912  136145
River Rch & RM=G103-80-03,G103-80-03_0005     ,3540.637
   23828   54875   75723  137577
River Rch & RM=G103-80-03,G103-80-03_0005     ,1833.788
   24023   55308   76372  138724
River Rch & RM=G103-80-03,G103-80-03_0005     ,464.682
   24100   55480   76630  139180
Boundary for River Rch & Prof#=G103-80-03,G103-80-03_0005     , 1
Up Type= 0
Dn Type= 3
Dn Slope=.0044
Boundary for River Rch & Prof#=G103-80-03,G103-80-03_0005     , 2
Up Type= 0
Dn Type= 3
Dn Slope=.0044
Boundary for River Rch & Prof#=G103-80-03,G103-80-03_0005     , 3
Up Type= 0
Dn Type= 3
Dn Slope=.0044
Boundary for River Rch & Prof#=G 03-80-03,G103-80-03_0005     , 4
Up Type= 0
Dn Type= 3
Dn Slope=.0044
DSS Import GetInterval= 0
DSS Import GetPeak= 0
DSS Import FillOption= 0

--- G103-80-03.g01 (geometry) ---

Geom Title=G103-80-03 June 2007
Version=Version 3.0.1  Mar 2001

River Reach=G103-80-03     ,G103-80-03_0005
Reach XY= 30
     3178095.982    13970012.461     3178151.024    13969708.803
     3178302.916    13969413.483        3178395.    13969308.759
     3178667.794    13969147.755     3178743.287    13969046.588
     3179014.725    13968199.201     3179197.858    13967925.654
       3179372.7     13967585.72     3179411.389    13967445.679
     3179424.239    13967295.421     3179333.698     13966368.77
     3179356.795    13966148.094     3179436.867    13965945.613
     3179548.553    13965761.519     3179933.285    13965264.127
     3179977.684    13965173.294     3180052.614    13964970.199
     3180152.371    13964578.836     3180326.995    13964085.395
     3180507.187    13963441.768      3180689.54    13963091.002
     3180909.242    13962828.596     3181154.713    13962610.297
     3181714.037    13961921.069     3182124.329    13961521.379
     3182353.328     13961175.76     3182885.068    13960940.242
     3184337.091    13960503.895     3184679.256    13960378.761

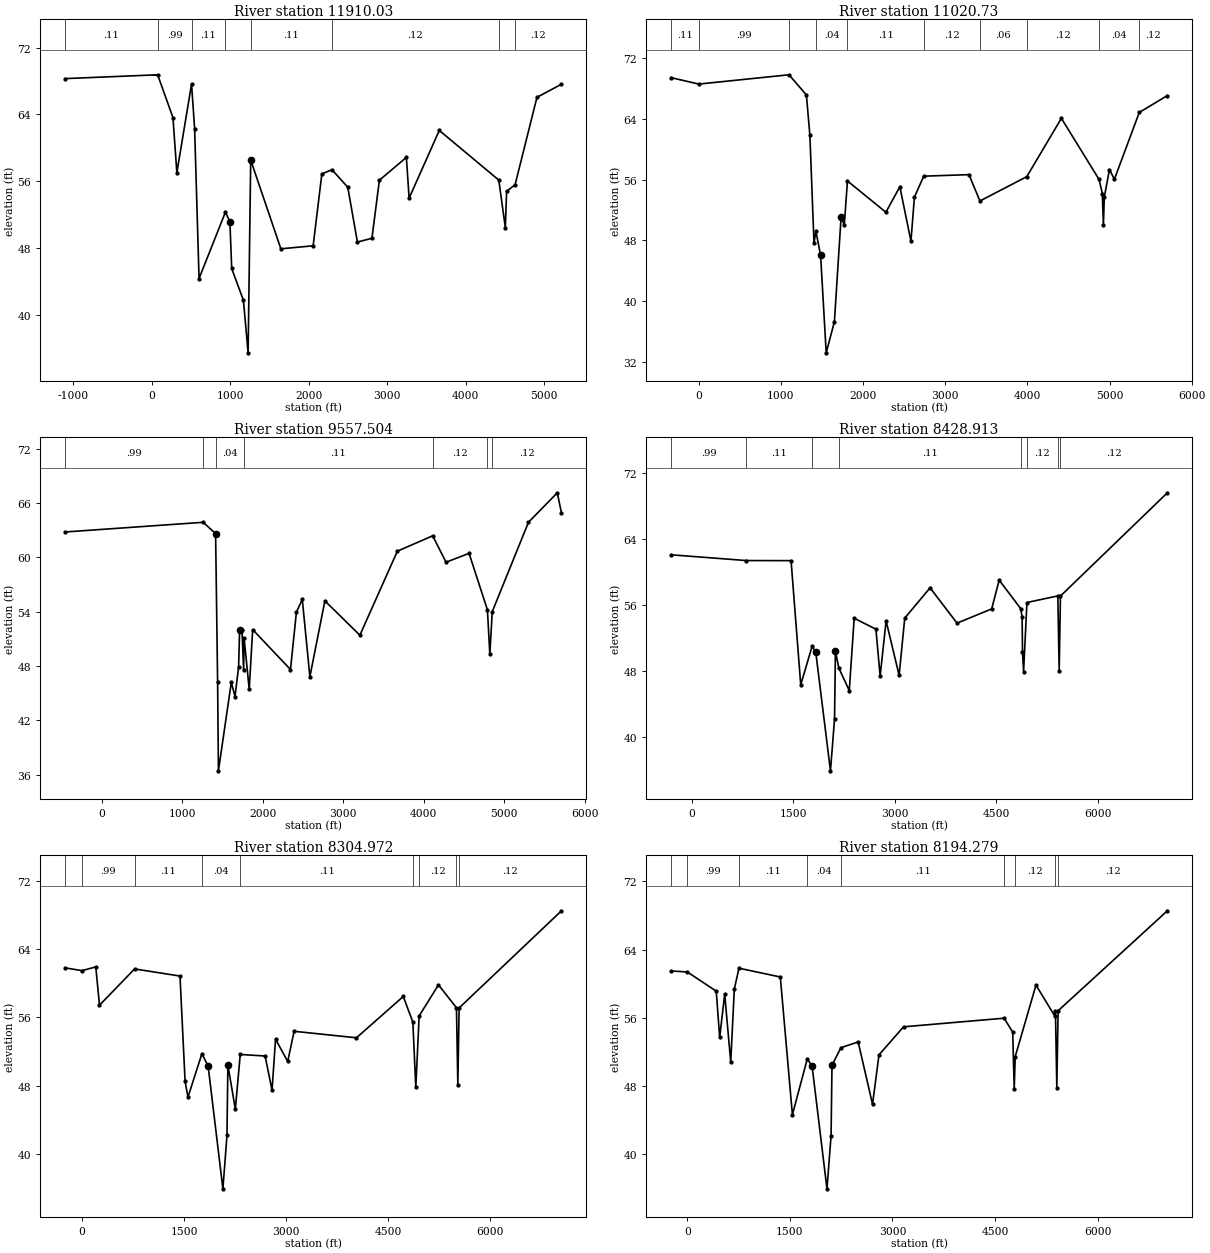
Type RM Length L Ch R = 1 ,11910.03,963.84,889.3,769.04
BEGIN DESCRIPTION:
412v1 and 413v7
Evaluated Manning's values and added survey for White Oak (413v7)
Block set in ROB to eliminate flow from a low area that is out of the influence area.
Bank Station offset =      3771
END DESCRIPTION:
XS GIS Cut Line= 6
 3180118.958762213970825.1710743     3177960.433    13968983.959
     3177077.144    13968067.649     3176697.413    13967613.622
     3175982.594    13966949.054     3175528.911    13966488.598
#Sta/Elev= 30
   -1104    68.3   76.82   68.76   271.7   63.63  321.64   57.03  508.75   67.64
   547.9   62.28  604.29   44.34  939.68   52.29  997.11   51.14 1020.11   45.54
 1169.11   41.73 1229.11   35.43 1262.11   58.54 1646.39    47.9 2057.34   48.26
 2168.33   56.88    2297   57.38 2498.11   55.29 2621.27   48.71 2806.26   49.16
 2900.94   56.12    3245   58.86 3279.65   53.97 3663.84   62.09 4421.79   56.14
 4505.18   50.45  4521.6    54.8 4629.55   55.58 4908.12   66.06 5220.45   67.63
#Mann= 8 ,-1 , 0
   -1104     .11       0   76.82     .99       0  508.75     .11       0
  939.68     .04       0 1262.11     .11       0    2297     .12       0
 4421.79     .06       0 4629.55     .12       0
#Block Obstruct= 2 , 0
       0   76.82   68.76 5103.93       0   68.64
Bank Sta=997.11,1262.11
XS Rating Curve= 0
Exp/Cntr=.3,.1

Type RM Length L Ch R = 1 ,11020.73,1535.48,1463.23,1125.97
BEGIN DESCRIPTION:
412v2 and either 413v2
Evaluated Manning's values and added survey for White Oak (413v2)
Adj elevations per slope between the known channel inverts
Block set in ROB to eliminate flow from a low area that is out of the influence area.
Bank Station offset =      3449
END DESCRIPTION:
XS GIS Cut Line= 6
 3180733.1070122    13969170.079     3180392.657    13969170.079
     3178507.202    13968495.467     3177122.214    13967570.147
     3176199.167       13966712.     3175589.675    13966254.223
#Sta/Elev= 30
 -340.45    69.4       0   68.55 1098.39   69.77 1310.07   67.12 1352.52   61.82
 1402.49   47.67 1426.06   49.21 1483.11   46.04  1551.1   33.24  1651.1   37.34
 1732.09   51.03 1771.16   50.04 1809.83   55.82 2277.71   51.71 2447.57   55.06
 2582.77   47.91 2624.85   53.69 2738.04   56.45 3288.88   56.65 3422.55   53.19
 3992.98   56.39 4414.04   64.05 4872.58   56.02 4912.58   54.17 4925.58   50.02
 4936.58   53.72 4999.58   57.32 5059.27   56.04    5362   64.82 5704.25   67.04
#Mann= 10 ,-1 , 0
 -340.45     .11       0       0     .99       0 1098.39     .11       0
 1426.06     .04       0 1809.83     .11       0 2738.04     .12       0
 3422.55     .06       0 3992.98     .12       0 4872.58     .04       0
    5362     .12       0
#Block Obstruct= 2 , 0
       0                 5560.06       0      69
Bank Sta=1483.11,1732.09
XS Rating Curve= 0
Exp/Cntr=.3,.1

Type RM Length L Ch R = 1 ,9557.504,940.33,1128.59,1306.92
BEGIN DESCRIPTION:
412v3 and 413v2
Evaluated Manning's values and added survey for White Oak (413v2)
Bank Station offset =      3548
Blocks set on LOB at EF San Jacinto watershed divide
Block set in ROB to eliminate flow from a low area that is out of the influence area.
END DESCRIPTION:
XS GIS Cut Line= 6
 3181387.656794313967550.9010585     3179686.458    13967328.076
      3178828.97    13967302.833     3178089.675    13967217.765
     3177282.383    13966931.306       3175667.8    13965768.112
#Sta/Elev= 30
 -454.61    62.8 1262.26   63.87 1416.78   62.62 1441.78   46.19 1451.78   36.42
 1611.78   46.19 1657.78   44.62 1702.78   47.92 1714.78   51.92 1744.78   51.92
 1764.78   47.52 1770.97   51.07  1834.3   45.42    1877   52.02 2346.91   47.61
 2420.49   53.95  2493.5   55.35 2587.79   46.82 2774.06   55.19 3208.76    51.4
  3674.4   60.68 4113.22   62.38  4278.6   59.46 4564.82   60.44 4792.85    54.2
 4822.85    49.3 4852.85      54 5302.43   63.87 5660.63   67.13 5712.81   64.89
#Mann= 7 ,-1 , 0
 -454.61     .99       0 1262.26     .11       0 1416.78     .04       0
 1770.97     .11       0 4113.22     .12       0 4792.85     .06       0
 4852.85     .12       0
#Block Obstruct= 2 , 0
       0    -454      69 5660.63       0      69
Bank Sta=1416.78,1714.78
XS Rating Curve= 0
Exp/Cntr=.3,.1

Type RM Length L Ch R = 1 ,8428.913,137.2,123.94,114.83
BEGIN DESCRIPTION:
412v4, 413s2d, and 414s2d
Evaluated Manning's values and added survey for White Oak (413s2d) and Mills Branch (414s2d)
Adj elevations per slope between the known channel inverts
Bank Station offset =      2948
Blocks set on LOB at EF San Jacinto watershed divide
END DESCRIPTION:
XS GIS Cut Line= 6
  3181476.45900913967088.7584148     3179161.724    13966111.652
     3178250.265    13965807.833     3177191.238    13965538.735
     3176896.099    13965382.485     3175524.571    13963368.597
#Sta/Elev= 30
 -306.96    62.1  809.83    61.4 1469.92   61.39 1612.98   46.37  1781.7   51.05
 1835.01   50.31 2052.18   35.96 2112.28    42.2 2125.46   50.44 2175.67    48.4
 2330.31   45.67 2402.72   54.42 2723.67    53.1  2786.3   47.42 2874.19    54.1
 3066.79   47.52  3149.8   54.44 3524.44    58.1 3922.45   53.83 4434.48   55.55
  4545.4   59.03 4862.75  55.595  4884.4  54.595 4889.83  50.385 4906.01  47.975
 4955.47  56.325 5411.91  57.125 5431.98  48.095 5450.83  57.105 7030.68    69.6
#Mann= 8 ,-1 , 0
 -306.96     .99       0  809.83     .11       0  1781.7     .04       0
 2175.67     .11       0 4862.75     .06       0 4955.47     .12       0
 5411.91     .06       0 5450.83     .12       0
#Block Obstruct= 2 , 0
       0    -300      68               0
Bank Sta=1835.01,2125.46
XS Rating Curve= 0
Exp/Cntr=.3,.1

Type RM Length L Ch R = 1 ,8304.972,99.46,110.69,114.26
BEGIN DESCRIPTION:
412v4, 413s2d, and 414s2d
Increased Manning's values inside the White Oak Creek and Mills Branch channels to represent the presence of  structure
Added survey for White Oak (413s2d) and Mills Branch (414s2d)
Adj elevations per slope between the known channel inverts
This section should be along Hueni Road in ROB (based on SIDS).
Blocks set on LOB at EF San Jacinto watershed divide.
Bank Station offset =      2928
END DESCRIPTION:
XS GIS Cut Line= 6
  3181492.14800313966957.8426715     3179170.404    13965994.465
      3178317.54    13965708.006     3177188.604    13965458.635
     3176844.015    13965228.406     3175611.377      13963266.6
#Sta/Elev= 30
 -251.56    61.8       0   61.47  202.19   61.91   256.9   57.43  773.19   61.67
 1441.02   60.84 1516.13   48.51 1558.42   46.68  1763.2   51.76 1854.88   50.31
 2072.05   35.96 2132.15    42.2 2145.33   50.44 2255.02   45.27 2327.42   51.67
 2693.11   51.49 2794.88   47.48 2846.63   53.46 3025.57   50.85 3119.53   54.38
 4036.64   53.62 4725.46   58.45  4866.4   55.45 4909.66   47.83 4959.12   56.18
 5243.44   59.81 5507.93   57.13    5528    48.1 5546.85   57.11 7052.78   68.47
#Mann= 9 ,-1 , 0
 -251.56     .11       0       0     .99       0  773.19     .11       0
  1763.2     .04       0 2327.42     .11       0  4866.4     .08       0
 4959.12     .12       0 5507.93     .08       0 5546.85     .12       0
#Block Obstruct= 2 , 0
       0    -247      68               0
Bank Sta=1854.88,2145.33
XS Rating Curve= 0
Exp/Cntr=.3,.1

Type RM Length L Ch R = 1 ,8194.279,1029.02,1018.74,955.4
BEGIN DESCRIPTION:
412v4, 413s2d, and 414s2d
Evaluated Manning's values and added survey for White Oak (413s2d) and Mills Branch (414s2d)
Adj elevations per slope between the known channel inverts
Bank Station offset =      2958
Blocks set on LOB at EF San Jacinto watershed divide
END DESCRIPTION:
XS GIS Cut Line= 6
  3181510.50300513966865.5008928     3179222.488    13965885.958
     3178354.432     13965608.18     3177668.668    13965495.333
     3176948.182    13965226.235      3175672.14    13963203.666
#Sta/Elev= 30
 -241.17    61.5       0   61.38  423.24   59.13   473.4   53.71  546.81   58.78
  635.04   50.81  687.27   59.37  755.55   61.82 1359.95   60.79  1536.8   44.65
 1755.02   51.21 1825.23   50.31  2042.4   35.96  2102.5    42.2 2115.68   50.44
 2246.43    52.5 2498.38   53.18 2708.57   45.87 2803.15   51.66 3161.92   54.95
 4633.26   55.96 4758.67   54.32 4780.28    47.7 4795.55   51.47 5098.81   59.84
 5371.69   56.24 5383.35   56.85 5403.42   47.82 5422.27   56.83  7020.1   68.55
#Mann= 9 ,-1 , 0
 -241.17     .11       0       0     .99       0  755.55     .11       0
 1755.02     .04       0 2246.43     .11       0 4633.26     .06       0
 4795.55     .12       0 5371.69     .06       0 5422.27     .12       0
#Block Obstruct= 2 , 0
       0    -236      69               0
Bank Sta=1825.23,2115.68
XS Rating Curve= 0
Exp/Cntr=.3,.1

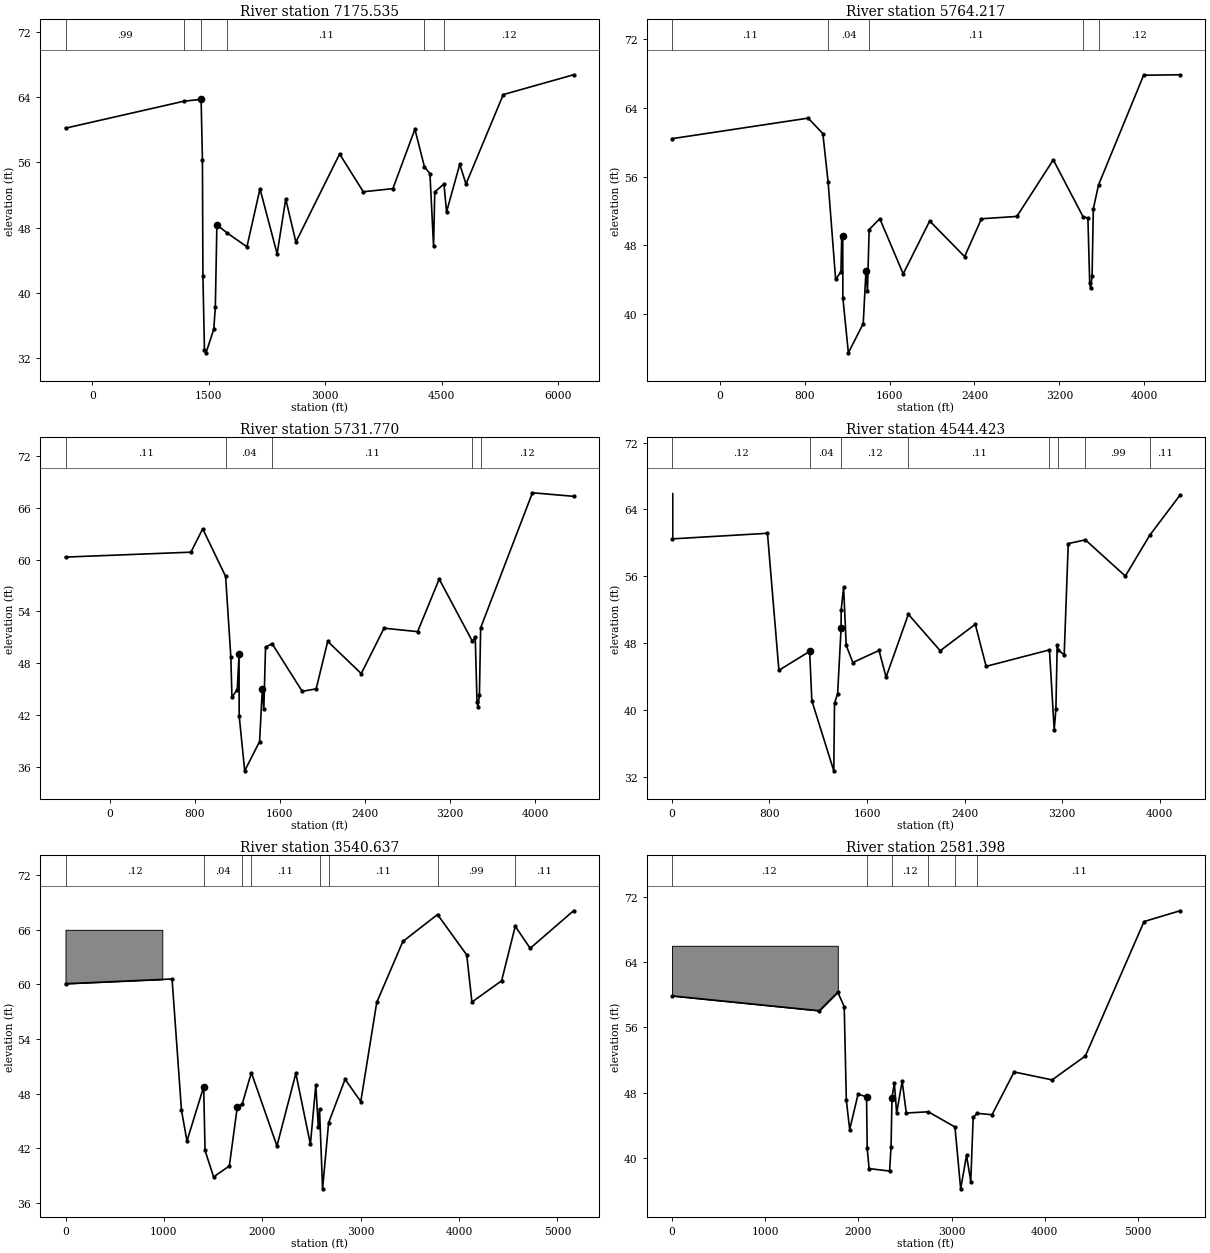
Type RM Length L Ch R = 1 ,7175.535,1430.82,1411.32,1344.85
BEGIN DESCRIPTION:
412v5 and 413v4
Evaluated Manning's values and added survey for White Oak (413v4)
Bank Station offset =      3517
Blocks set on LOB at EF San Jacinto watershed divide
END DESCRIPTION:
XS GIS Cut Line= 6
 3181724.667809913965783.4480101     3180125.265    13965174.152
     3177807.557    13964410.263      3177225.96    13964271.374
     3176974.224    13964271.374     3175880.474    13963186.305
#Sta/Elev= 30
 -346.03    60.2 1175.24    63.5 1400.39   63.74 1417.39   56.24 1423.64   42.04
 1443.39   32.94 1463.39   32.64 1563.39   35.54 1583.39   38.24 1603.39   48.34
 1734.99   47.35 1990.35   45.65 2158.42   52.76 2379.05   44.79 2490.19   51.51
 2620.71   46.23 3183.76   57.03 3488.63    52.4 3869.93   52.78 4153.47   60.07
 4275.82   55.47 4347.02   54.63 4393.59   45.74 4409.26   52.38  4527.6   53.35
 4560.94   49.93 4730.97   55.77 4811.31   53.35 5291.35   64.32 6196.41   66.75
#Mann= 6 ,-1 , 0
 -346.03     .99       0 1175.24     .11       0 1400.39     .04       0
 1734.99     .11       0 4275.82     .06       0  4527.6     .12       0
#Block Obstruct= 2 , 0
       0    -341      68               0
Bank Sta=1400.39,1603.39
XS Rating Curve= 0
Exp/Cntr=.3,.1

Type RM Length L Ch R = 1 ,5764.217,28.19,32.45,24.2
BEGIN DESCRIPTION:
412v6 and 413s3u
Evaluated Manning's values and added survey for White Oak (413s3u)
Bank Station offset =      3789
Blocks set on LOB at EF San Jacinto watershed divide
END DESCRIPTION:
XS GIS Cut Line= 6
 3182039.484986913964294.2946137     3181101.864     13963946.16
     3180578.484    13963817.877     3179895.207    13963705.302
     3178690.335    13963600.709     3178190.069    13962356.804
#Sta/Elev= 30
 -451.85    60.4  832.29   62.79  970.58   60.99  1020.3   55.35 1091.19   44.03
 1141.19   44.93 1148.19   48.83 1158.19   49.03 1159.19    41.9 1211.19    35.5
 1351.19    38.9 1377.19   45.03 1391.19   42.73 1407.19   49.83 1507.41    51.1
 1728.14   44.68 1977.65   50.83 2307.13   46.69 2465.87   51.09 2799.58   51.36
 3143.02   57.94 3423.05   51.34 3469.47   51.16 3486.33    43.6  3495.5   43.07
 3508.76    44.4 3520.48   52.24 3569.37   55.02 3994.86   67.78 4337.79   67.83
#Mann= 5 ,-1 , 0
 -451.85     .11       0  1020.3     .04       0 1407.19     .11       0
 3423.05     .06       0 3569.37     .12       0
#Block Obstruct= 2 , 0
       0    -446      67               0
Bank Sta=1158.19,1377.19
XS Rating Curve= 0
Exp/Cntr=.3,.1

Type RM Length L Ch R = 1 ,5731.770,1102.79,1187.35,1486.04
BEGIN DESCRIPTION:
412v6 and 413s3u
Evaluated Manning's values and added survey for White Oak (413s3u)
Bank Station offset =      3730
Blocks set on LOB at EF San Jacinto watershed divide
END DESCRIPTION:
XS GIS Cut Line= 6
 3182070.070269913964275.9004312     3181175.434    13963926.678
     3180596.105    13963792.987     3179961.072    13963688.262
      3178733.34    13963581.309       3178243.8    13962333.777
#Sta/Elev= 30
 -415.02    60.3   764.6   60.87  875.53   63.58  1090.9   58.06 1139.97   48.75
 1150.44   44.03 1200.44   44.93 1217.44   49.03 1218.44    41.9 1270.44    35.5
 1410.44    38.9 1436.44   45.03 1450.44   42.73 1466.44   49.83 1527.26   50.27
 1811.04   44.73  1942.5   45.01 2051.47   50.52 2366.76   46.78 2581.02   52.05
 2897.22   51.65 3099.85   57.75 3412.62  50.515 3438.86  51.015 3455.72  43.455
 3464.89  42.925 3478.15  44.255 3489.87  52.095 3976.98   67.76 4363.59   67.35
#Mann= 5 ,-1 , 0
 -415.02     .11       0  1090.9     .04       0 1527.26     .11       0
 3412.62     .06       0 3489.87     .12       0
#Block Obstruct= 2 , 0
       0    -410      67               0
Bank Sta=1217.44,1436.44
XS Rating Curve= 0
Exp/Cntr=.3,.1

Type RM Length L Ch R = 1 ,4544.423,1048.94,1003.79,945.32
BEGIN DESCRIPTION:
412v7 and 415 v10 (This section d/s as in model *.g03 in Caney-White Oak Combination directory)
Bank Station offset =      3673
Blocks set on LOB at EF San Jacinto watershed divide
END DESCRIPTION:
XS GIS Cut Line= 6
     3181966.751    13963513.716     3181001.821    13962749.377
     3179948.988    13961788.261     3179812.047    13961430.355
     3179710.056    13961094.471     3179379.817    13960391.801
#Sta/Elev= 30
       0   60.48  783.37   61.15  877.21   44.75 1129.49   47.01 1147.49   41.11
 1327.49   32.71 1333.49   40.81 1358.92   41.93 1387.49   49.81 1387.89   51.95
 1408.14   54.68 1429.54   47.72 1483.79   45.68  1698.7   47.12 1756.47   43.93
 1939.25   51.45 2200.57   47.09 2488.49   50.26 2577.03   45.22 3096.71   47.19
 3135.71   37.61 3149.71   40.12 3160.21   47.77 3167.71   47.19 3217.71    46.6
 3250.92   59.92 3391.45   60.36 3719.37   56.03 3919.31   60.91 4167.85   65.72
#Mann= 8 ,-1 , 0
       0     .12       0 1129.49     .04       0 1387.89     .12       0
 1939.25     .11       0 3096.71     .04       0 3167.71     .11       0
 3391.45     .99       0 3919.31     .11       0
#Block Obstruct= 2 , 0
       0       5      66               0
Bank Sta=1129.49,1387.49
XS Rating Curve= 0
Exp/Cntr=.3,.1

Type RM Length L Ch R = 1 ,3540.637,847.67,959.24,1052.03
BEGIN DESCRIPTION:
412v8
Bank Station offset =      3435
Blocks set on LOB at EF San Jacinto watershed divide
END DESCRIPTION:
XS GIS Cut Line= 6
     3182097.047    13963339.306     3182120.075    13962471.941
     3181949.454    13962164.492     3181328.566    13961775.815
     3179666.151    13960175.252      3178994.55    13959571.846
#Sta/Elev= 30
       0   60.08 1083.23    60.6 1178.65    46.2 1234.61   42.81 1404.63   48.77
 1418.33   41.77 1505.33   38.87 1665.33   40.07 1746.33   46.57 1796.33   46.87
 1889.14   50.32 2149.34   42.27 2341.32   50.24 2489.28   42.45 2544.04   48.94
 2570.04   44.32 2582.04    46.3 2613.04   37.56 2674.54   44.82 2841.93   49.59
 3001.45   47.14 3163.56   58.03    3429   64.72 3781.25   67.68 4078.33   63.24
 4131.21   58.07 4432.81    60.4  4571.4   66.39 4723.06   63.97 5164.09   68.09
#Mann= 8 ,-1 , 0
       0     .12       0 1404.63     .04       0 1796.33     .12       0
 1889.14     .11       0 2582.04     .04       0 2674.54     .11       0
 3781.25     .99       0  4571.4     .11       0
#Block Obstruct= 2 , 0
       0  983.72      66               0
Bank Sta=1404.63,1746.33
XS Rating Curve= 0
Exp/Cntr=.3,.1

Type RM Length L Ch R = 1 ,2581.398,686.99,747.61,893.2
BEGIN DESCRIPTION:
412v9
Bank Station offset =      2665
Blocks set on LOB at EF San Jacinto watershed divide
END DESCRIPTION:
XS GIS Cut Line= 6
     3182181.481    13963370.009     3182509.055    13961582.819
      3182150.98    13961115.697     3181861.323    13960832.684
     3181954.464    13960383.539     3180830.542    13958518.908
#Sta/Elev= 30
       0   59.86  1581.1   58.04 1779.09   60.31 1848.12   58.55 1870.82   47.06
  1906.8   43.49 1996.63   47.81 2087.79    47.5 2094.79    41.2 2114.79    38.7
 2334.79    38.4 2350.79    41.4 2360.79    47.4 2385.79    49.2 2410.79    45.5
 2469.87   49.42 2514.04   45.51 2750.42   45.66 3036.29    43.8 3097.65   36.22
 3160.54   40.32 3206.13   37.11 3231.84   44.98 3274.61   45.47 3434.05    45.3
 3671.28   50.54 4078.69   49.57 4435.78    52.5 5065.33   68.97 5451.15   70.29
#Mann= 6 ,-1 , 0
       0     .12       0 2087.79     .04       0 2360.79     .12       0
 2750.42     .11       0 3036.29     .04       0 3274.61     .11       0
#Block Obstruct= 2 , 0
       0 1779.09      66               0
Bank Sta=2087.79,2360.79
XS Rating Curve= 0
Exp/Cntr=.3,.1

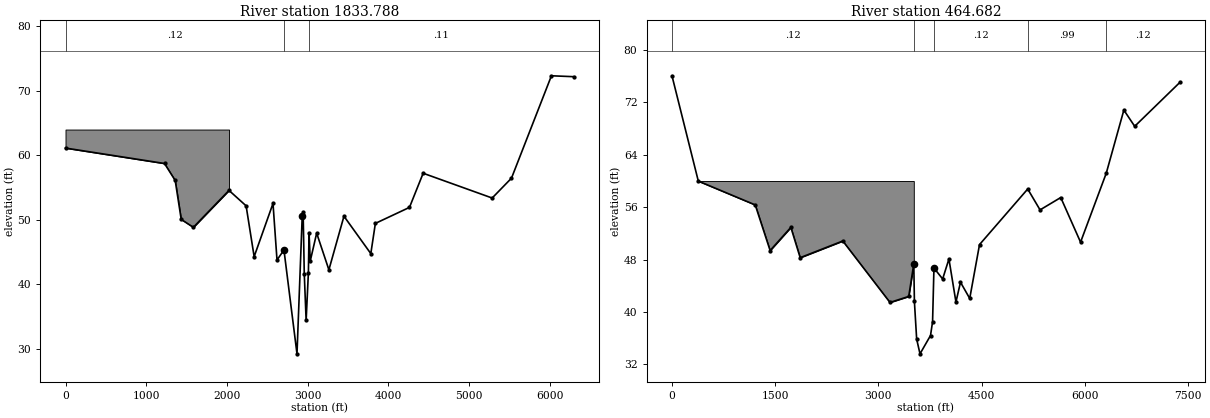
Type RM Length L Ch R = 1 ,1833.788,1369.11,1369.11,1335.14
BEGIN DESCRIPTION:
412v10
Bank Station offset =      2131
Blocks set on LOB at EF San Jacinto watershed divide
END DESCRIPTION:
XS GIS Cut Line= 6
     3182651.486    13963619.018       3183125.7    13961437.987
     3182861.915    13960786.961     3182918.127    13959967.679
      3182757.23    13959357.555     3181245.034    13958219.552
#Sta/Elev= 30
       0   61.13 1227.19   58.74 1359.67   56.11  1434.3   50.08 1584.58   48.85
 2026.48   54.57 2238.73   52.18 2338.35   44.31 2572.01   52.55  2621.6   43.79
 2707.89   45.34  2869.4   29.25 2934.49   50.68  2945.4   51.24 2959.69   41.63
 2982.69   34.43 3010.69   41.83 3018.69   48.03 3033.69   43.63 3113.21   47.95
 3264.77   42.27 3451.57   50.57 3784.47   44.78  3840.9   49.46 4263.68   51.94
 4433.19   57.23 5288.59   53.39 5528.26   56.47 6023.34   72.33 6297.42   72.19
#Mann= 3 ,-1 , 0
       0     .12       0 2707.89     .04       0 3018.69     .11       0
#Block Obstruct= 2 , 0
       0 2026.48      64               0
Bank Sta=2707.89,2934.49
XS Rating Curve= 0
Exp/Cntr=.3,.1

Type RM Length L Ch R = 1 ,464.682 ,340.28,464.68,999.62
BEGIN DESCRIPTION:
412v11
Bank Station offset =      1395
Blocks set on LOB at EF San Jacinto watershed divide
END DESCRIPTION:
XS GIS Cut Line= 6
     3187500.807    13961472.293      3186981.88    13961167.706
     3184724.004    13961123.014     3184287.248    13960683.885
     3183834.477    13959633.487     3181613.472    13958012.306
#Sta/Elev= 30
       0   76.08  382.86   59.99 1210.18   56.35 1426.55   49.38 1728.05   52.92
 1863.64   48.29 2483.17   50.84 3169.01   41.45 3441.52   42.37 3515.11   47.34
 3523.88    41.6 3556.66   35.85 3605.34    33.6 3758.05    36.4 3788.02   38.51
 3808.01   46.71 3934.48   45.04 4025.77   48.09 4127.66   41.52 4193.72   44.54
 4328.09   42.06 4470.44   50.29 5170.92   58.78 5350.31   55.59 5651.19   57.48
 5939.02   50.66 6312.78    61.2 6568.38   70.84 6726.04   68.36 7384.69   75.09
#Mann= 5 ,-1 , 0
       0     .12       0 3515.11     .04       0 3808.01     .12       0
 5170.92     .99       0 6312.78     .12       0
#Block Obstruct= 2 , 0
       0 3515.11      60               0
Bank Sta=3515.11,3808.01
XS Rating Curve= 0
Exp/Cntr=.3,.1

Chan Stop Cuts=-1